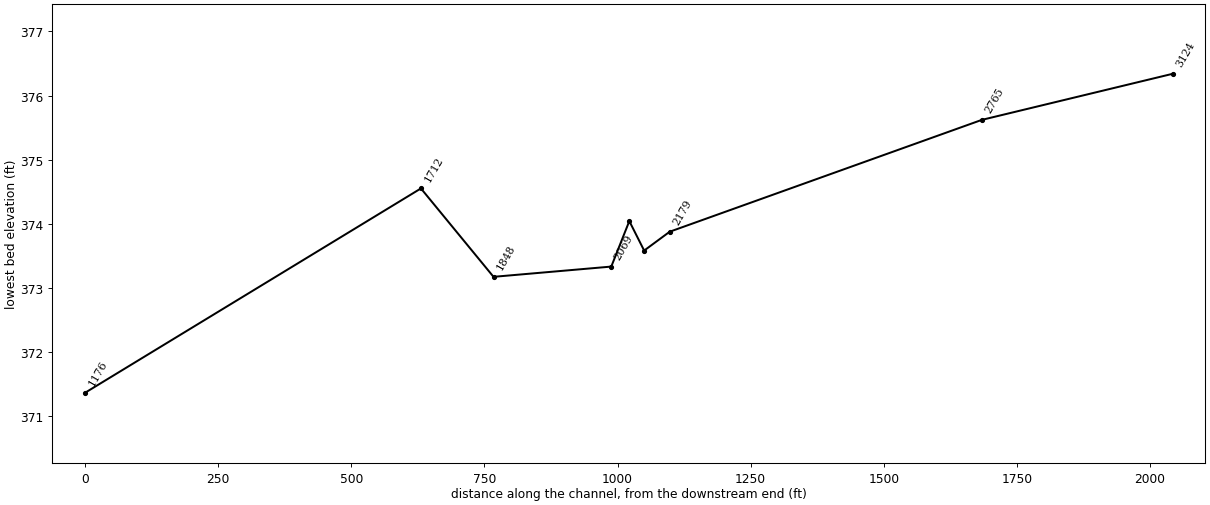
--- MadisonCo.prj (project) ---

Proj Title=Madison Co HEC-RAS
Current Plan=p01
Default Exp/Contr=0.3,0.1
English Units
Geom File=g01
Geom File=g03
Geom File=g04
Flow File=f01
Plan File=p01
Plan File=p02
Plan File=p04
Y Axis Title=Elevation
X Axis Title(PF)=Main Channel Distance
X Axis Title(XS)=Station
BEGIN DESCRIPTION:
END DESCRIPTION:
DSS File=..\MadisonCo.dss
DSS Export Rating Curves= 0
DSS Export Rating Curve Sorted= 0
DSS Export Volume Flow Curves= 0
DXF Filename=..\..\..\TDOT - Bridges - HEC-RAS\HEC-RAS\Madison Co\Madison Co - HEC-RAS\Madison Co HEC-RAS.
DXF OffsetX= 0
DXF OffsetY= 0
DXF ScaleX= 1
DXF ScaleY= 10

--- MadisonCo.p01 (plan) ---

Plan Title=NATURAL
Program Version=5.06
Short Identifier=NATURAL
Geom File=g03
Flow File=f01
Subcritical Flow
K Sum by GR= 0
Std Step Tol= 0.01
Critical Tol= 0.01
Num of Std Step Trials= 20
Max Error Tol= 0.3
Flow Tol Ratio= 0.001
Split Flow NTrial= 30
Split Flow Tol= 0.02
Split Flow Ratio= 0.02
Log Output Level= 0
Friction Slope Method= 1
Unsteady Friction Slope Method= 2
Unsteady Bridges Friction Slope Method= 1
Parabolic Critical Depth
Global Vel Dist= 0 , 0 , 0
Global Log Level= 0
CheckData=True
Encroach Param=-1 ,0,0, 0
Computation Interval=1MIN
Output Interval=1HOUR
Instantaneous Interval=1HOUR
Mapping Interval=1HOUR
Computation Time Step Use Courant=        0
Computation Time Step Use Time Series=    0
Computation Time Step Count To Double=0
Computation Time Step Max Doubling=0
Computation Time Step Max Halving=0
Computation Time Step Residence Courant=0
Run HTab= 0
Run UNet= 0
Run Sediment= 0
Run PostProcess= 0
Run WQNet= 0
Run RASMapper= 0
UNET Theta= 1
UNET Theta Warmup= 1
UNET ZTol= 0.02
UNET ZSATol= 0.02
UNET MxIter= 20
UNET Max Iter WO Improvement= 0
UNET MaxInSteps= 0
UNET DtIC= 0
UNET DtMin= 0
UNET MaxCRTS= 20
UNET WFStab= 2
UNET SFStab= 1
UNET WFX= 1
UNET SFX= 1
UNET 1D Methodology=Finite Difference
UNET DSS MLevel= 4
UNET Pardiso=0
UNET DZMax Abort= 100
UNET Use Existing IB Tables=-1
UNET Froude Reduction=False
UNET Froude Limit= 0.8
UNET Froude Power= 4
UNET D1 Cores= 0
UNET D2 Coriolis=0
UNET D2 Cores= 0
UNET D2 Theta= 1
UNET D2 Theta Warmup= 1
UNET D2 Z Tol= 0.01
UNET D2 Volume Tol= 0.01
UNET D2 Max Iterations= 20
UNET D2 Equation= 0
UNET D2 RampUpFraction=0.1
UNET D2 TimeSlices= 1
UNET D2 BCVolumeCheck=0
UNET D1D2 MaxIter= 0
UNET D1D2 ZTol=0.01
UNET D1D2 QTol=0.1
UNET D1D2 MinQTol=1
Write IC File= 0
Write IC File at Fixed DateTime=0
Write IC File at Sim End=0
Echo Input=False
Echo Parameters=False
Echo Output=False
Write Detailed= 0
HDF Write Warmup=0
HDF Write Time Slices=0
HDF Flush=0
HDF Face Node Velocities=0
HDF Compression= 1
HDF Chunk Size= 1
HDF Spatial Parts= 1
HDF Use Max Rows=0
HDF Fixed Rows= 1
Calibration Method= 0
Calibration Iterations= 20
Calibration Max Change=0.05
Calibration Tolerance=0.2
Calibration Maximum=1.5
Calibration Minimum=0.5
Calibration Optimization Method= 1
WQ AD Non Conservative
WQ ULTIMATE=-1
WQ Max Comp Step=1HOUR
WQ Output Interval=15MIN
WQ Output Selected Increments= 0
WQ Output face flow=0
WQ Output face velocity=0
WQ Output face area=0
WQ Output face dispersion=0
WQ Output cell volume=0
WQ Output cell surface area=0
WQ Output cell continuity=0
WQ Output cumulative cell continuity=0
WQ Output face conc=0
WQ Output face dconc_dx=0
WQ Output face courant=0
WQ Output face peclet=0
WQ Output face adv mass=0
WQ Output face disp mass=0
WQ Output cell mass=0
WQ Output cell source sink temp=0
WQ Output nsm pathways=0
WQ Output nsm derived pathways=0
WQ Output MaxMinRange=-1
WQ Daily Max Min Mean=-1
WQ Daily Range=0
WQ Daily Time=0
WQ Create Restart=0
WQ Fixed Restart=0
WQ System Summary=0
WQ Write To DSS=0
WQ Use Fixed Temperature=0
Sorting and Armoring Iterations= 10
XS Update Threshold= 0.02
Bed Roughness Predictor= 0
Hydraulics Update Threshold= 0.02
Energy Slope Method= 1
Volume Change Method= 1
Sediment Retention Method= 0
XS Weighting Method= 0
Number of US Weighted Cross Sections= 1
Number of DS Weighted Cross Sections= 1
Upstream XS Weight=0
Main XS Weight=1
Downstream XS Weight=0
Number of DS XS's Weighted with US Boundary= 1
Upstream Boundary Weight= 1
Weight of XSs Associated with US Boundary= 0
Number of US XS's Weighted with DS Boundary= 1
Downstream Boundary Weight= 0.5
Weight of XSs Associated with DS Boundary= 0.5
Percentile Method= 0
Sediment Output Level= 3
Mass or Volume Output= 0
Output Increment Type= 1
Profile and TS Output Increment= 1
XS Output Flag= 0
XS Output Increment= 10
Write Gradation File= 0
Read Gradation Hotstart= 0
Write HDF5 File= 1
Write Binary Output= 1
Write DSS Sediment File= 0
SV Curve= 0
Specific Gage Flag= 0

--- MadisonCo.p02 (plan) ---

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Plan Title=EXISTING
Short Identifier=EXISTING
Geom File=g01
Flow File=f01

--- MadisonCo.p04 (plan) ---

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Plan Title=PROPOSED
Short Identifier=PROPOSED
Geom File=g04
Flow File=f01

--- MadisonCo.f01 (steady flow) ---

Flow Title=MadisonCo
Program Version=5.06
BEGIN FILE DESCRIPTION:
Unknown Branch of Chisholm Creek
END FILE DESCRIPTION:
Number of Profiles= 7
Profile Names=Q2,Q5,Q10,Q25,Q50,Q100,Q500
River Rch & RM=Chisholm Creek,Unnamed Branch  ,3124
     377     532     631     752     839     922    1120
Boundary for River Rch & Prof#=Chisholm Creek,Unnamed Branch  , 1
Up Type= 0
Dn Type= 3
Dn Slope=0.004542
DSS Import GetInterval= 0
DSS Import GetPeak= 0
DSS Import FillOption= 0

--- MadisonCo.g03 (geometry) ---

Geom Title=Natural
Program Version=5.06

River Reach=Chisholm Creek  ,Unnamed Branch
Reach XY= 5
0.847510373443980.238589211618260.667012448132780.46265560165975
0.554979253112030.408713692946060.218879668049790.79045643153527
0.184238391212270.86456844751296

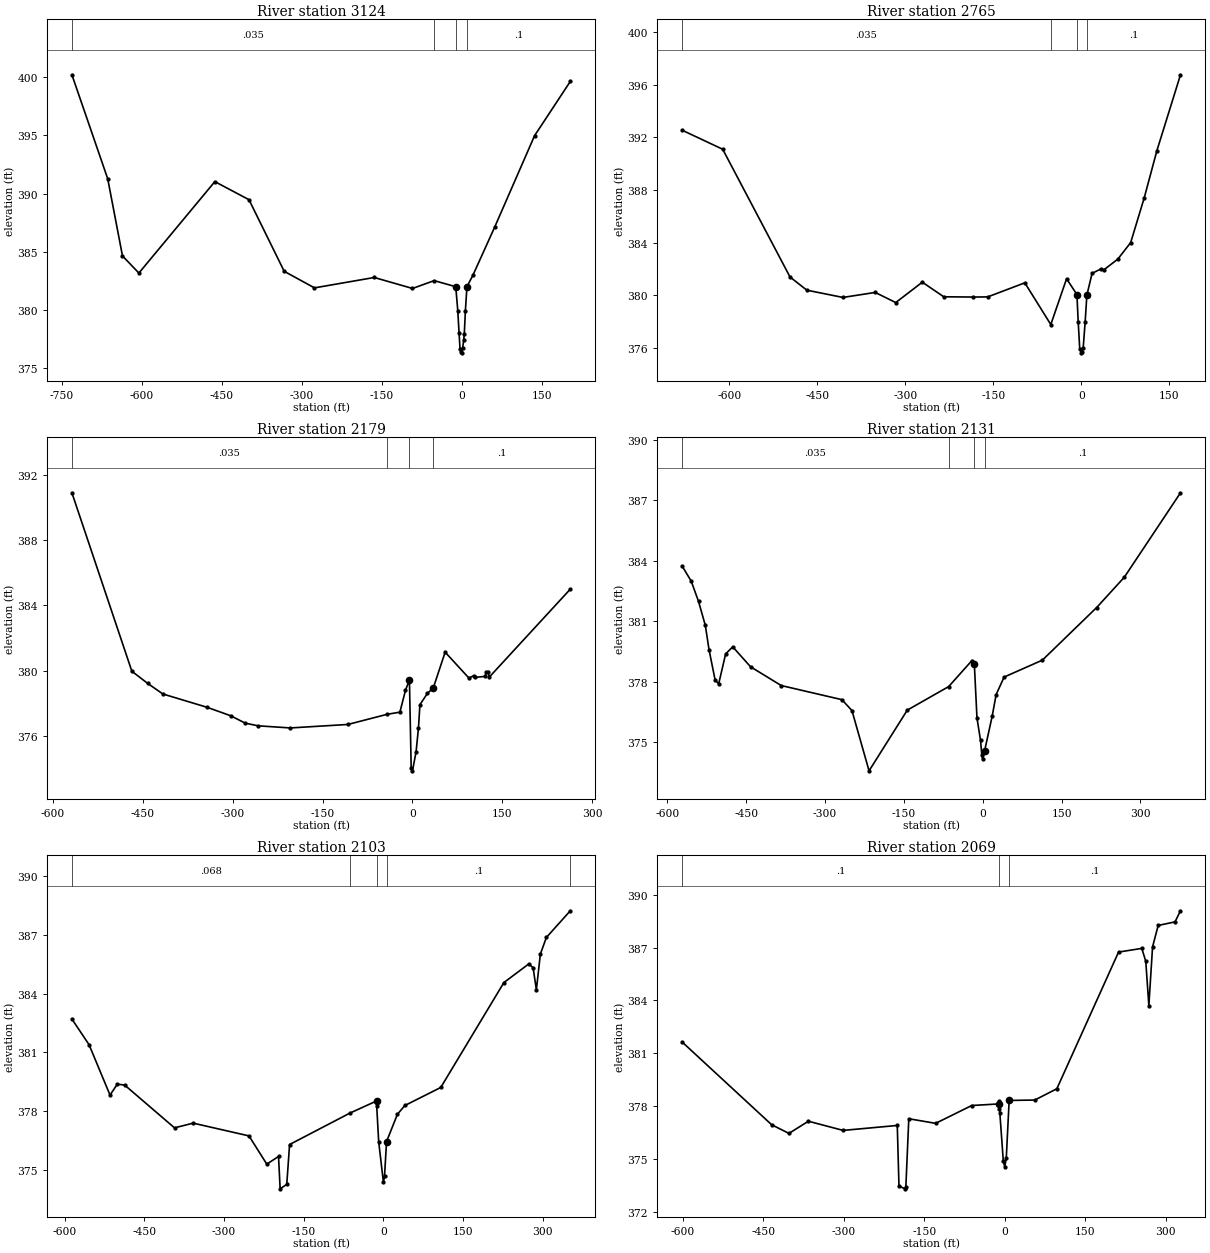
Type RM Length L Ch R = 1 ,3124    ,355.04,358.65,361.84
BEGIN DESCRIPTION:
LiDAR1
END DESCRIPTION:
#Sta/Elev= 26
 -730.69  400.18 -663.51  391.26 -635.87  384.65  -605.1  383.18 -462.71  391.02
 -398.69  389.47 -332.67  383.33 -275.91  381.91 -163.86   382.8  -92.14  381.86
  -51.43  382.53  -11.08  382.01   -7.26  379.97    -4.8     378   -3.04  376.71
   -1.34  376.41       0  376.34    1.87  376.75    3.88  377.44    5.01  377.99
    7.05  379.97    9.92  382.01   21.31  383.01   61.75   387.1  136.76  394.96
  203.74  399.61
#Mann= 4 ,-1 , 0
 -730.69    .035       0  -51.43      .1       0  -11.08    .048       0
    9.92      .1       0
#XS Ineff= 2 , 0
Permanent Ineff=
       T       T
Bank Sta=-11.08,9.92
XS Rating Curve= 0 ,0
Exp/Cntr=0.3,0.1

Type RM Length L Ch R = 1 ,2765    ,605.86,586.09,559.53
BEGIN DESCRIPTION:
LiDAR2
END DESCRIPTION:
#Sta/Elev= 30
 -680.61  392.54 -611.35  391.09 -496.56  381.38 -467.83  380.38 -406.39  379.83
 -351.34  380.21 -316.39  379.44 -271.07  380.99 -234.54  379.88 -184.99  379.86
 -159.62  379.87  -96.34  380.94  -52.04  377.77  -25.14  381.25   -7.52  380.05
   -5.33  377.97   -2.73  375.94       0  375.62    1.47  375.65    3.18     376
    6.58     378    9.42     380   18.31  381.66   33.54     382   38.49  381.93
   62.18  382.74   84.14     384   107.3  387.41  128.85  390.99  169.05  396.75
#Mann= 4 ,-1 , 0
 -680.61    .035       0  -52.04      .1       0   -7.52    .048       0
    9.42      .1       0
#XS Ineff= 2 , 0
Permanent Ineff=
       T       F
Bank Sta=-7.52,9.42
XS Rating Curve= 0 ,0
Exp/Cntr=0.3,0.1

Type RM Length L Ch R = 1 ,2179    ,52.96,47.99,48.26
BEGIN DESCRIPTION:
UP1
END DESCRIPTION:
#Sta/Elev= 30
 -568.07   390.9 -468.07379.9721 -441.92379.2351  -416.4378.5809 -342.34 377.762
  -303.2377.2474 -279.05376.7951 -257.41376.6304 -203.64 376.501 -107.75376.7142
   -42.5377.3342     -21377.4676  -11.71378.7999   -5.11379.4407   -2.17374.0624
       0373.8743    6.04375.0491   10.03376.5201   12.42377.9272   24.98378.6197
   34.66378.9472   54.47381.1406    94.1379.5568  102.34379.7044  103.65 379.599
  121.53 379.656  122.74379.9471  126.41379.9018  128.04379.6105  263.26     385
#Mann= 4 ,-1 , 0
 -568.07    .035       0   -42.5      .1       0   -5.11    .048       0
   34.66      .1       0
#XS Ineff= 2 , 0
Permanent Ineff=
       T       T
Bank Sta=-5.11,34.66
XS Rating Curve= 0 ,0
Exp/Cntr=0.3,0.1

Type RM Length L Ch R = 1 ,2131    ,24.09,27.86,28.68
BEGIN DESCRIPTION:
UP2
END DESCRIPTION:
#Sta/Elev= 30
 -571.96  383.74 -554.61  382.99 -540.63  381.98 -527.69  380.79 -520.69  379.59
 -509.22   378.1 -502.35  377.89 -489.06  379.38 -475.56  379.73 -441.64  378.74
 -383.28  377.81 -267.89  377.11 -248.77  376.57  -216.2  373.58 -143.49  376.59
  -64.66  377.76  -20.47  379.05  -15.94378.8928  -10.87376.1967   -4.15375.0973
   -1.69374.3793       0374.1657     3.6  374.57   18.06  376.29   25.56  377.36
   40.72  378.23  113.56  379.07  216.87  381.68  269.38  383.18  376.34  387.37
#Mann= 4 ,-1 , 0
 -571.96    .035       0  -64.66      .1       0  -15.94    .048       0
     3.6      .1       0
#XS Ineff= 2 , 0
Permanent Ineff=
       T       T
Bank Sta=-15.94,3.6
XS Rating Curve= 0 ,0
Exp/Cntr=0.3,0.1

Type RM Length L Ch R = 1 ,2103    ,30.09,33.86,34.68
BEGIN DESCRIPTION:
NATURAL - SR223
END DESCRIPTION:
#Sta/Elev= 30
 -586.47   382.7 -554.16  381.39 -514.68  378.82 -500.97  379.38 -487.05  379.33
 -393.29  377.15 -358.15  377.39 -253.14  376.74 -219.55   375.3 -197.48  375.69
 -194.43  374.04 -181.96  374.27 -176.66   376.3  -63.25   377.9  -13.01  378.52
  -12.69  378.28   -8.87  376.43       0  374.37    2.06  374.68    5.91  376.45
    26.3  377.84   40.37  378.29  107.97  379.21   226.8  384.56  273.69  385.51
  281.75  385.32  287.95  384.19  295.44  386.01  306.78  386.86  351.85  388.22
#Mann= 5 ,-1 , 0
 -586.47    .068       0  -63.25    .076       0  -12.69    .048       0
    5.91      .1       0  351.85      .1       0
#XS Ineff= 2 , 0
Permanent Ineff=
       T       T
Bank Sta=-13.01,5.91
XS Rating Curve= 0 ,0
Exp/Cntr=0.3,0.1

Type RM Length L Ch R = 1 ,2069    ,220.1,221.15,221.05
BEGIN DESCRIPTION:
DOWN1
END DESCRIPTION:
#Sta/Elev= 30
 -600.99  381.65  -434.1  376.96 -401.92  376.47 -365.72  377.16    -301  376.64
 -200.15  376.92 -197.01  373.49 -185.81  373.33 -184.16  373.45  -178.7   377.3
 -128.68  377.04  -61.49  378.05  -10.06378.1417   -9.82377.8753   -9.78378.3173
   -9.15377.6436   -2.64374.8964       0374.5825    2.86375.0637    8.23378.3363
   55.99  378.36   97.08     379     212  386.74  255.26  386.95   262.7  386.22
  268.42  383.71  275.33  387.03  285.79  388.25  317.14  388.45  327.37  389.08
#Mann= 3 , 0 , 0
 -600.99      .1       0  -10.06    .048       0    8.23      .1       0
#XS Ineff= 2 , 0
Permanent Ineff=
       T       F
Bank Sta=-10.06,8.23
XS Rating Curve= 0 ,0
Exp/Cntr=0.3,0.1

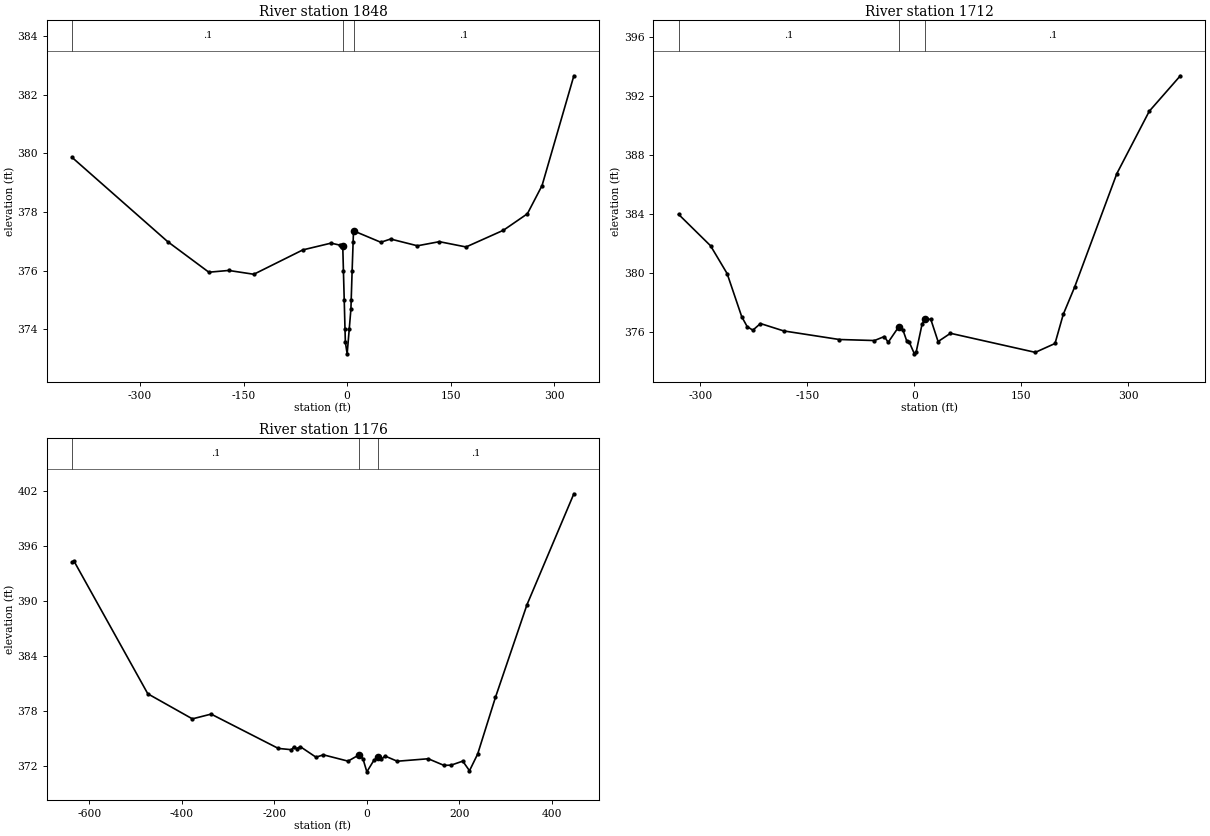
Type RM Length L Ch R = 1 ,1848    ,137.88,136.32,136.5
BEGIN DESCRIPTION:
STA 1848
END DESCRIPTION:
#Sta/Elev= 29
 -398.37  379.86 -259.84  376.99 -200.27  375.95 -171.54  376.01 -135.17  375.88
  -64.17  376.71  -23.38  376.94  -10.02  376.87   -6.38  376.85   -5.38  375.99
   -4.23     375   -3.09     374    -2.6  373.57       0  373.17    2.99     374
    5.47   374.7    5.88  375.02    7.21     376    8.65  376.98    9.21  377.36
   48.76  376.97   62.91  377.08  101.75  376.85  133.53  376.99  172.18  376.81
  226.39  377.38  261.02  377.94  282.24   378.9  328.32  382.64
#Mann= 3 , 0 , 0
 -398.37      .1       0   -6.38    .048       0    9.21      .1       0
#XS Ineff= 2 , 0
Permanent Ineff=
       T       T
Bank Sta=-6.38,9.21
XS Rating Curve= 0 ,0
Exp/Cntr=0.3,0.1

Type RM Length L Ch R = 1 ,1712    ,628.29,630.76,602.03
BEGIN DESCRIPTION:
LiDAR3
END DESCRIPTION:
#Sta/Elev= 30
 -330.58  383.99 -285.68  381.86 -262.48  379.98 -241.99  377.06 -234.34  376.39
  -226.4  376.15 -215.76   376.6 -183.17   376.1  -105.3  375.52  -55.96  375.45
  -42.13  375.72  -36.73  375.33  -21.92  376.38   -15.8  376.13   -10.9  375.45
   -7.36  375.36       0  374.55    2.63   374.7   10.91  376.59   15.51  376.91
   23.05  376.88   33.23  375.38    50.6  375.94  169.52  374.65  197.13  375.25
  208.67  377.22  224.57  379.06  283.75  386.74   329.2  390.96  372.77  393.36
#Mann= 3 , 0 , 0
 -330.58      .1       0  -21.92    .048       0   15.51      .1       0
#XS Ineff= 2 , 0
Permanent Ineff=
       T       T
Bank Sta=-21.92,15.51
XS Rating Curve= 0 ,0
Exp/Cntr=0.3,0.1

Type RM Length L Ch R = 1 ,1176    ,0,0,0
BEGIN DESCRIPTION:
LiDAR4
END DESCRIPTION:
#Sta/Elev= 30
 -637.25  394.28 -633.23   394.4 -473.52  379.89 -377.16  377.15 -336.63  377.67
 -191.42  373.92 -162.96  373.78  -157.7  374.08  -151.9  373.89 -143.77  374.11
 -109.91  372.96     -94  373.22  -40.67  372.53  -17.08  373.21   -8.39  372.79
       0  371.36   14.97   372.6   23.64  373.01    31.5  372.73   39.18  373.09
    65.7  372.52  132.74  372.79  166.53  372.07  182.05  372.09  207.32  372.53
  221.89  371.48  239.51   373.3  277.92  379.49  346.19  389.63  447.51  401.75
#Mann= 3 , 0 , 0
 -637.25      .1       0  -17.08    .048       0   23.64      .1       0
Bank Sta=-17.08,23.64
XS Rating Curve= 0 ,0
Exp/Cntr=0.3,0.1
LCMann Table=0

Chan Stop Cuts=-1
Use User Specified Reach Order=0
Composite Channel Slope=5

--- MadisonCo.g01 (geometry) ---

Geom Title=Existing
Program Version=5.06

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
River Reach=Chisholm Creek  ,Unnamed Branch

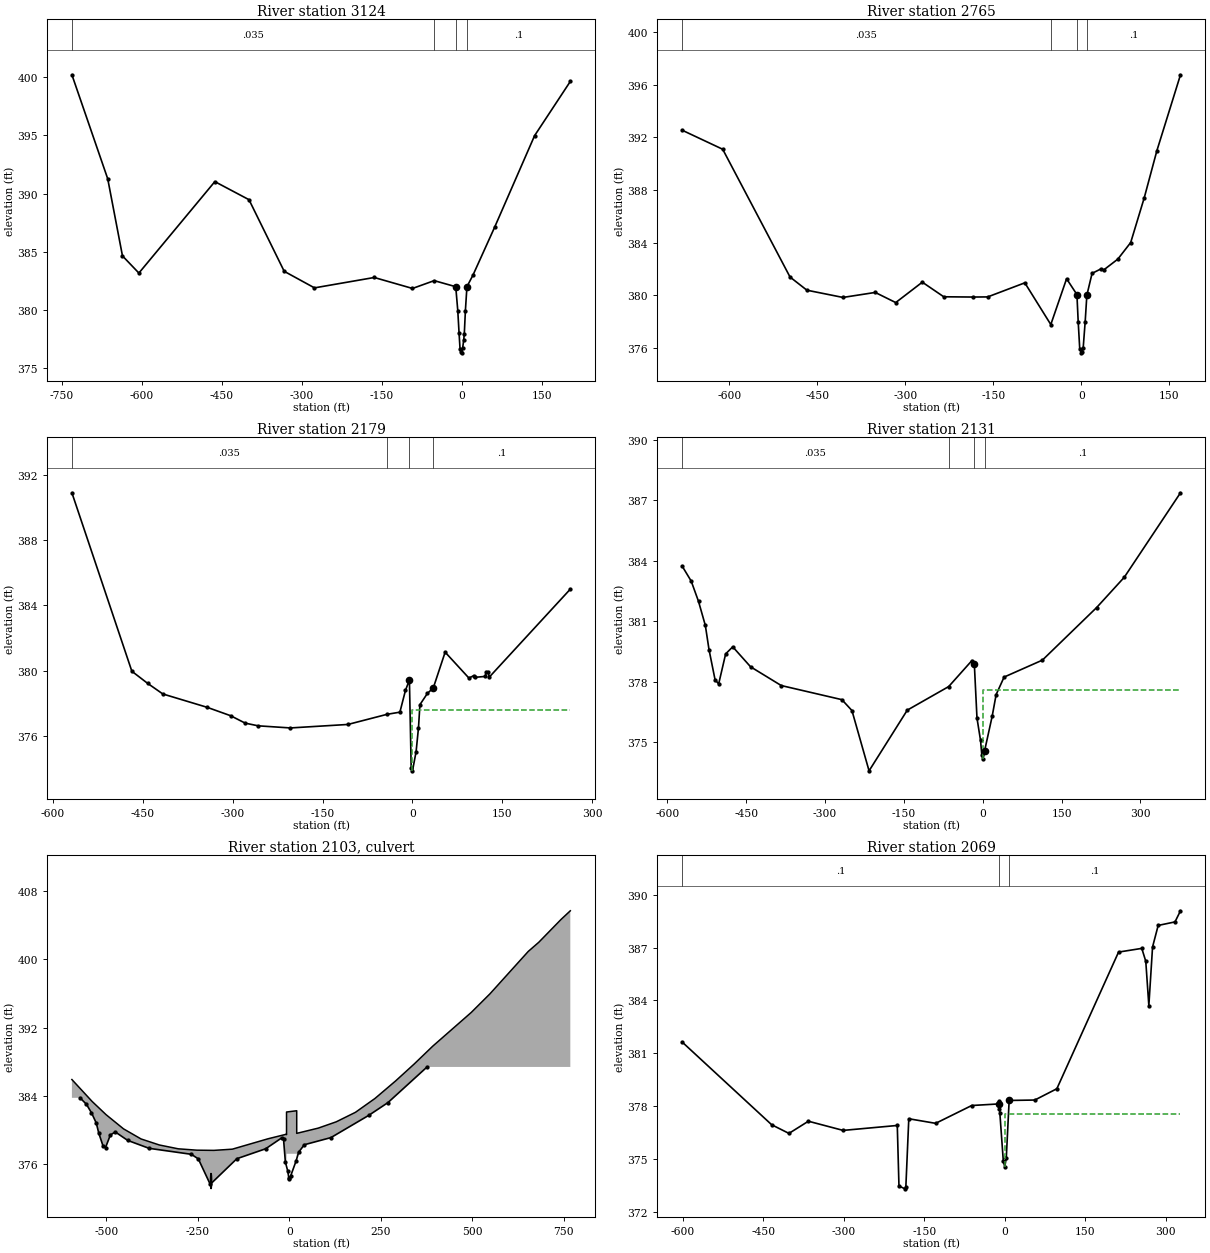
Type RM Length L Ch R = 1 ,3124    ,355.04,358.65,361.84
BEGIN DESCRIPTION:
LiDAR1
END DESCRIPTION:
#Sta/Elev= 26
 -730.69  400.18 -663.51  391.26 -635.87  384.65  -605.1  383.18 -462.71  391.02
 -398.69  389.47 -332.67  383.33 -275.91  381.91 -163.86   382.8  -92.14  381.86
  -51.43  382.53  -11.08  382.01   -7.26  379.97    -4.8     378   -3.04  376.71
   -1.34  376.41       0  376.34    1.87  376.75    3.88  377.44    5.01  377.99
    7.05  379.97    9.92  382.01   21.31  383.01   61.75   387.1  136.76  394.96
  203.74  399.61
#Mann= 4 ,-1 , 0
 -730.69    .035       0  -51.43      .1       0  -11.08    .048       0
    9.92      .1       0
Bank Sta=-11.08,9.92
XS Rating Curve= 0 ,0
Exp/Cntr=0.3,0.1

Type RM Length L Ch R = 1 ,2765    ,605.86,586.09,559.53
BEGIN DESCRIPTION:
LiDAR2
END DESCRIPTION:
#Sta/Elev= 30
 -680.61  392.54 -611.35  391.09 -496.56  381.38 -467.83  380.38 -406.39  379.83
 -351.34  380.21 -316.39  379.44 -271.07  380.99 -234.54  379.88 -184.99  379.86
 -159.62  379.87  -96.34  380.94  -52.04  377.77  -25.14  381.25   -7.52  380.05
   -5.33  377.97   -2.73  375.94       0  375.62    1.47  375.65    3.18     376
    6.58     378    9.42     380   18.31  381.66   33.54     382   38.49  381.93
   62.18  382.74   84.14     384   107.3  387.41  128.85  390.99  169.05  396.75
#Mann= 4 ,-1 , 0
 -680.61    .035       0  -52.04      .1       0   -7.52    .048       0
    9.42      .1       0
Bank Sta=-7.52,9.42
XS Rating Curve= 0 ,0
Exp/Cntr=0.3,0.1

Type RM Length L Ch R = 1 ,2179    ,52.96,47.99,48.26
BEGIN DESCRIPTION:
UP1
END DESCRIPTION:
#Sta/Elev= 30
 -568.07   390.9 -468.07379.9721 -441.92379.2351  -416.4378.5809 -342.34 377.762
  -303.2377.2474 -279.05376.7951 -257.41376.6304 -203.64 376.501 -107.75376.7142
   -42.5377.3342     -21377.4676  -11.71378.7999   -5.11379.4407   -2.17374.0624
       0373.8743    6.04375.0491   10.03376.5201   12.42377.9272   24.98378.6197
   34.66378.9472   54.47381.1406    94.1379.5568  102.34379.7044  103.65 379.599
  121.53 379.656  122.74379.9471  126.41379.9018  128.04379.6105  263.26     385
#Mann= 4 ,-1 , 0
 -568.07    .035       0   -42.5      .1       0   -5.11    .048       0
   34.66      .1       0
#XS Ineff= 2 , 0
       0 -272.44  377.57   78.65       0  377.57
Permanent Ineff=
       F       F
Bank Sta=-5.11,34.66
XS Rating Curve= 0 ,0
Exp/Cntr=0.5,0.3

Type RM Length L Ch R = 1 ,2131    ,54.19,61.72,63.36
BEGIN DESCRIPTION:
UP2
END DESCRIPTION:
#Sta/Elev= 30
 -571.96  383.74 -554.61  382.99 -540.63  381.98 -527.69  380.79 -520.69  379.59
 -509.22   378.1 -502.35  377.89 -489.06  379.38 -475.56  379.73 -441.64  378.74
 -383.28  377.81 -267.89  377.11 -248.77  376.57  -216.2  373.58 -143.49  376.59
  -64.66  377.76  -20.47  379.05  -15.94378.8928  -10.87376.1967   -4.15375.0973
   -1.69374.3793       0374.1657     3.6  374.57   18.06  376.29   25.56  377.36
   40.72  378.23  113.56  379.07  216.87  381.68  269.38  383.18  376.34  387.37
#Mann= 4 ,-1 , 0
 -571.96    .035       0  -64.66      .1       0  -15.94    .048       0
     3.6      .1       0
#XS Ineff= 2 , 0
       0 -224.44  377.57   30.65       0  377.57
Permanent Ineff=
       F       F
Bank Sta=-15.94,3.6
XS Rating Curve= 0 ,0
Exp/Cntr=0.5,0.3

Type RM Length L Ch R = 2 ,2103    ,,,
BEGIN DESCRIPTION:
BRIDGE
END DESCRIPTION:
Bridge Culvert--1,0,-1,-1, 0
Deck Dist Width WeirC Skew NumUp NumDn MinLoCord MaxHiCord MaxSubmerge Is_Ogee
10.53,32.6,2.6,0, 29, 29, , , 0.98, 0, 4.86,4.86,,
 -594.18 -538.99  -500.9 -453.07 -405.22 -355.16 -303.52 -252.39 -206.13  -155.9
  -58.11   -8.19   -7.73   -7.72   20.12   20.13    78.8   128.1  180.62  233.95
  290.26  341.07  391.94   497.1  548.06  652.71  681.44  742.25  767.69
  385.89  383.32 381.768 380.096 378.912 378.204 377.754 377.594 377.571 377.712
 378.935 379.467 379.421382.0772382.2253 379.569 380.184 380.926 382.042 383.669
 385.725 387.715 389.816 393.776 395.957 400.936  402.01  404.69 405.711
     365     365     365     365     365     365     365     365     365     365
     365     365     365  377.17  377.17     365     365     365     365     365
     365     365     365     365     365     365     365     365     365
 -605.96 -550.77 -512.68 -464.85    -417 -366.94  -315.3 -264.17 -217.91 -167.68
  -69.89  -19.97  -19.51   -19.5    8.34    8.35   67.02  116.32  168.84  222.17
  278.48  329.29  380.16  485.32  536.28  640.93  669.66  730.47  755.91
  385.89  383.32 381.768 380.096 378.912 378.204 377.754 377.594 377.571 377.712
 378.935 379.467 379.421382.0772382.2253 379.569 380.184 380.926 382.042 383.669
 385.725 387.715 389.816 393.776 395.957 400.936  402.01  404.69 405.711
     365     365     365     365     365     365     365     365     365     365
     365     365     365  377.17  377.17     365     365     365     365     365
     365     365     365     365     365     365     365     365     365
BR Coef=-1 , 0 , 0 ,, 0 ,,,0.8,-1,,0,
WSPro=,,,, 1 ,,,, 0 ,,,, 0 ,,,,-1 ,-1 ,-1 , 0 , 0 , 0 , 0 , 0
Culvert=4,1.833,3.33,50.04,0.012,0.2,1,29,1,373.053,-213.91,372.591,-183.83,Culvert #1  , 0 ,4.68
 -213.91 -183.83
BC Culvert Barrel=1,40x22,0
Culvert Bottom n=0.012
BC Design=,, 0 ,, 0 ,,,,,,
BC Use User HTab Curves=0
BC User HTab FreeFlow(D)= 0

Type RM Length L Ch R = 1 ,2069    ,220.1,221.15,221.05
BEGIN DESCRIPTION:
DOWN1
END DESCRIPTION:
#Sta/Elev= 30
 -600.99  381.65  -434.1  376.96 -401.92  376.47 -365.72  377.16    -301  376.64
 -200.15  376.92 -197.01  373.49 -185.81  373.33 -184.16  373.45  -178.7   377.3
 -128.68  377.04  -61.49  378.05  -10.06378.1417   -9.82377.8753   -9.78378.3173
   -9.15377.6436   -2.64374.8964       0374.5825    2.86375.0637    8.23378.3363
   55.99  378.36   97.08     379     212  386.74  255.26  386.95   262.7  386.22
  268.42  383.71  275.33  387.03  285.79  388.25  317.14  388.45  327.37  389.08
#Mann= 3 , 0 , 0
 -600.99      .1       0  -10.06    .048       0    8.23      .1       0
#XS Ineff= 2 , 0
       0 -187.47  377.57  40.085       0  377.57
Permanent Ineff=
       F       F
Bank Sta=-10.06,8.23
XS Rating Curve= 0 ,0
Exp/Cntr=0.5,0.3

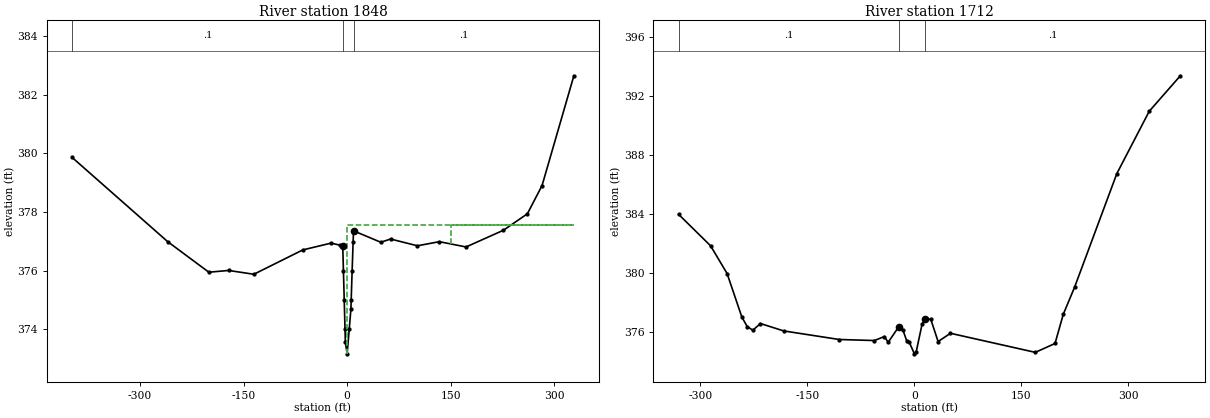
Type RM Length L Ch R = 1 ,1848    ,137.88,136.32,136.5
BEGIN DESCRIPTION:
STA 1848
END DESCRIPTION:
#Sta/Elev= 29
 -398.37  379.86 -259.84  376.99 -200.27  375.95 -171.54  376.01 -135.17  375.88
  -64.17  376.71  -23.38  376.94  -10.02  376.87   -6.38  376.85   -5.38  375.99
   -4.23     375   -3.09     374    -2.6  373.57       0  373.17    2.99     374
    5.47   374.7    5.88  375.02    7.21     376    8.65  376.98    9.21  377.36
   48.76  376.97   62.91  377.08  101.75  376.85  133.53  376.99  172.18  376.81
  226.39  377.38  261.02  377.94  282.24   378.9  328.32  382.64
#Mann= 3 , 0 , 0
 -398.37      .1       0   -6.38    .048       0    9.21      .1       0
#XS Ineff= 2 , 0
       0 -297.97  377.57 150.585       0  377.57
Permanent Ineff=
       F       F
Bank Sta=-6.38,9.21
XS Rating Curve= 0 ,0
Exp/Cntr=0.3,0.1

Type RM Length L Ch R = 1 ,1712    ,628.29,630.76,602.03
BEGIN DESCRIPTION:
LiDAR3
END DESCRIPTION:
#Sta/Elev= 30
 -330.58  383.99 -285.68  381.86 -262.48  379.98 -241.99  377.06 -234.34  376.39
  -226.4  376.15 -215.76   376.6 -183.17   376.1  -105.3  375.52  -55.96  375.45
  -42.13  375.72  -36.73  375.33  -21.92  376.38   -15.8  376.13   -10.9  375.45
   -7.36  375.36       0  374.55    2.63   374.7   10.91  376.59   15.51  376.91
   23.05  376.88   33.23  375.38    50.6  375.94  169.52  374.65  197.13  375.25
  208.67  377.22  224.57  379.06  283.75  386.74   329.2  390.96  372.77  393.36
#Mann= 3 , 0 , 0
 -330.58      .1       0  -21.92    .048       0   15.51      .1       0
Bank Sta=-21.92,15.51
XS Rating Curve= 0 ,0
Exp/Cntr=0.3,0.1

--- MadisonCo.g04 (geometry) ---

Geom Title=Proposed
Program Version=5.06

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
River Reach=Chisholm Creek  ,Unnamed Branch

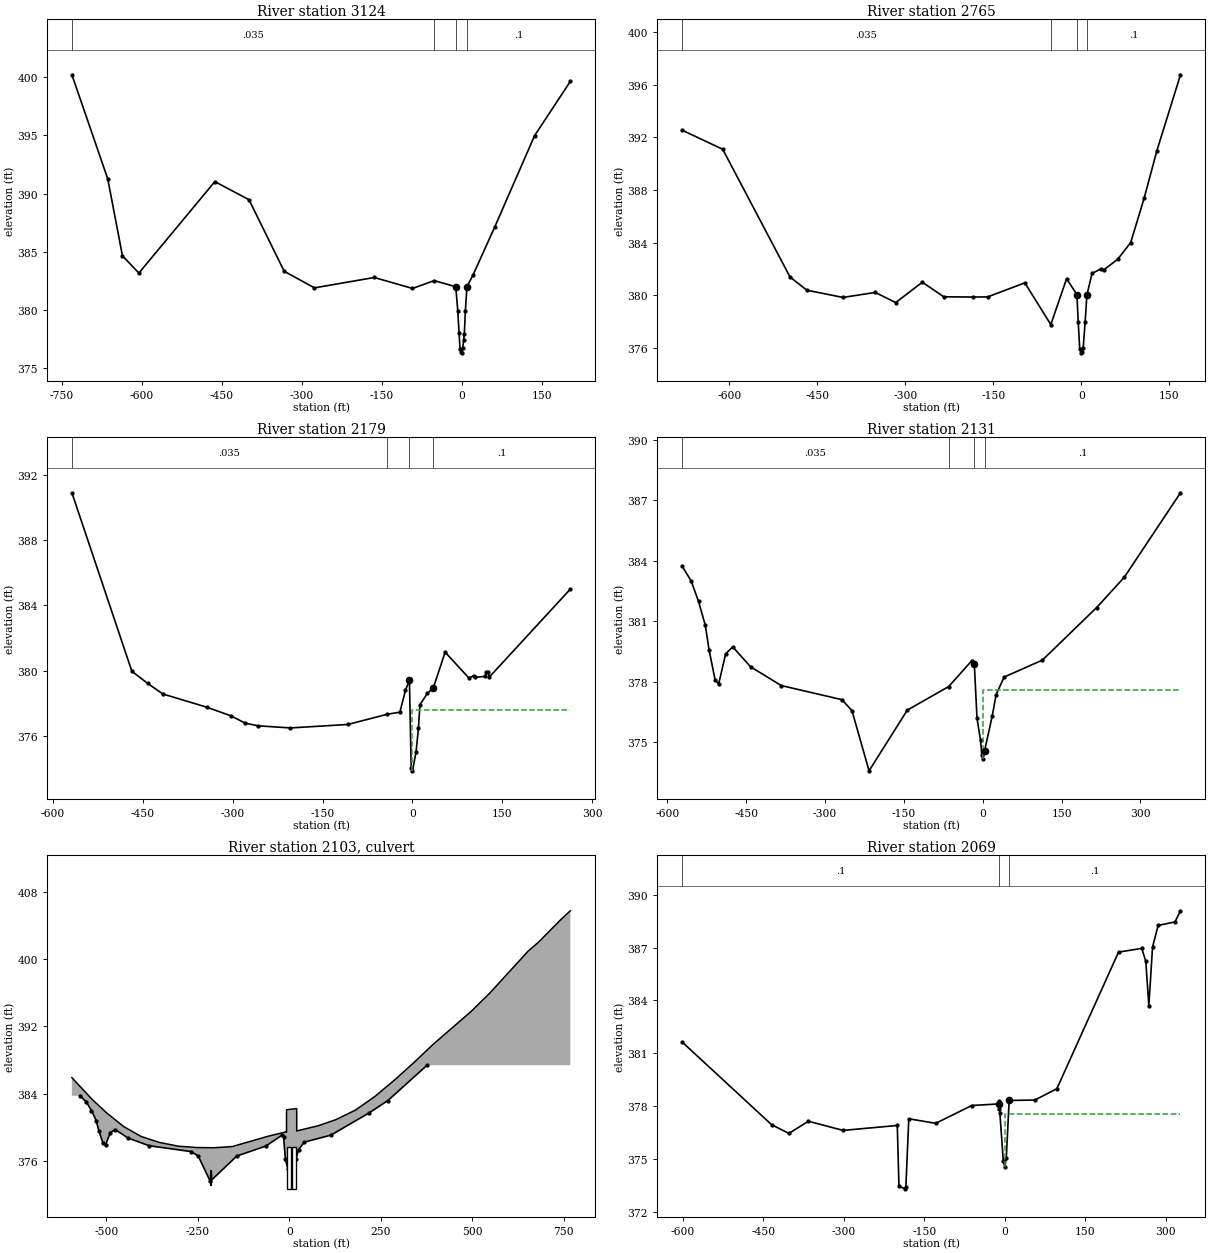
Type RM Length L Ch R = 1 ,3124    ,355.04,358.65,361.84
BEGIN DESCRIPTION:
LiDAR1
END DESCRIPTION:
#Sta/Elev= 26
 -730.69  400.18 -663.51  391.26 -635.87  384.65  -605.1  383.18 -462.71  391.02
 -398.69  389.47 -332.67  383.33 -275.91  381.91 -163.86   382.8  -92.14  381.86
  -51.43  382.53  -11.08  382.01   -7.26  379.97    -4.8     378   -3.04  376.71
   -1.34  376.41       0  376.34    1.87  376.75    3.88  377.44    5.01  377.99
    7.05  379.97    9.92  382.01   21.31  383.01   61.75   387.1  136.76  394.96
  203.74  399.61
#Mann= 4 ,-1 , 0
 -730.69    .035       0  -51.43      .1       0  -11.08    .048       0
    9.92      .1       0
Bank Sta=-11.08,9.92
XS Rating Curve= 0 ,0
Exp/Cntr=0.3,0.1

Type RM Length L Ch R = 1 ,2765    ,605.86,586.09,559.53
BEGIN DESCRIPTION:
LiDAR2
END DESCRIPTION:
#Sta/Elev= 30
 -680.61  392.54 -611.35  391.09 -496.56  381.38 -467.83  380.38 -406.39  379.83
 -351.34  380.21 -316.39  379.44 -271.07  380.99 -234.54  379.88 -184.99  379.86
 -159.62  379.87  -96.34  380.94  -52.04  377.77  -25.14  381.25   -7.52  380.05
   -5.33  377.97   -2.73  375.94       0  375.62    1.47  375.65    3.18     376
    6.58     378    9.42     380   18.31  381.66   33.54     382   38.49  381.93
   62.18  382.74   84.14     384   107.3  387.41  128.85  390.99  169.05  396.75
#Mann= 4 ,-1 , 0
 -680.61    .035       0  -52.04      .1       0   -7.52    .048       0
    9.42      .1       0
Bank Sta=-7.52,9.42
XS Rating Curve= 0 ,0
Exp/Cntr=0.3,0.1

Type RM Length L Ch R = 1 ,2179    ,52.96,47.99,48.26
BEGIN DESCRIPTION:
UP1
END DESCRIPTION:
#Sta/Elev= 30
 -568.07   390.9 -468.07379.9721 -441.92379.2351  -416.4378.5809 -342.34 377.762
  -303.2377.2474 -279.05376.7951 -257.41376.6304 -203.64 376.501 -107.75376.7142
   -42.5377.3342     -21377.4676  -11.71378.7999   -5.11379.4407   -2.17374.0624
       0373.8743    6.04375.0491   10.03376.5201   12.42377.9272   24.98378.6197
   34.66378.9472   54.47381.1406    94.1379.5568  102.34379.7044  103.65 379.599
  121.53 379.656  122.74379.9471  126.41379.9018  128.04379.6105  263.26     385
#Mann= 4 ,-1 , 0
 -568.07    .035       0   -42.5      .1       0   -5.11    .048       0
   34.66      .1       0
#XS Ineff= 2 , 0
       0  -271.8  377.57   66.89       0  377.57
Permanent Ineff=
       F       F
Bank Sta=-5.11,34.66
XS Rating Curve= 0 ,0
Exp/Cntr=0.5,0.3

Type RM Length L Ch R = 1 ,2131    ,54.19,61.72,63.36
BEGIN DESCRIPTION:
UP2
END DESCRIPTION:
#Sta/Elev= 30
 -571.96  383.74 -554.61  382.99 -540.63  381.98 -527.69  380.79 -520.69  379.59
 -509.22   378.1 -502.35  377.89 -489.06  379.38 -475.56  379.73 -441.64  378.74
 -383.28  377.81 -267.89  377.11 -248.77  376.57  -216.2  373.58 -143.49  376.59
  -64.66  377.76  -20.47  379.05  -15.94378.8928  -10.87376.1967   -4.15375.0973
   -1.69374.3793       0374.1657     3.6  374.57   18.06  376.29   25.56  377.36
   40.72  378.23  113.56  379.07  216.87  381.68  269.38  383.18  376.34  387.37
#Mann= 4 ,-1 , 0
 -571.96    .035       0  -64.66      .1       0  -15.94    .048       0
     3.6      .1       0
#XS Ineff= 2 , 0
       0  -223.8  377.57   29.42       0  377.57
Permanent Ineff=
       F       F
Bank Sta=-15.94,3.6
XS Rating Curve= 0 ,0
Exp/Cntr=0.5,0.3

Type RM Length L Ch R = 2 ,2103    ,,,
BEGIN DESCRIPTION:
BRIDGE
END DESCRIPTION:
Bridge Culvert--1,0,-1,-1, 0
Deck Dist Width WeirC Skew NumUp NumDn MinLoCord MaxHiCord MaxSubmerge Is_Ogee
10.53,32.6,2.6,0, 29, 29, , , 0.98, 0, 4.86,4.86,,
 -594.18 -538.99  -500.9 -453.07 -405.22 -355.16 -303.52 -252.39 -206.13  -155.9
  -58.11   -8.19   -7.73   -7.72   20.12   20.13    78.8  127.03  180.62  233.95
  290.26  341.07  391.94   497.1  548.06  652.71  681.44  742.25  767.69
  385.89  383.32 381.768 380.096 378.912 378.204 377.754 377.594 377.571 377.712
 378.935 379.467 379.421 382.077 382.225 379.569 380.184 380.906 382.042 383.669
 385.725 387.715 389.816 393.776 395.957 400.936  402.01  404.69 405.711
     365     365     365     365     365     365     365     365     365     365
     365     365     365     365     365     365     365     365     365     365
     365     365     365     365     365     365     365     365     365
 -605.96 -550.77 -512.68 -464.85    -417 -366.94  -315.3 -264.17 -217.91 -167.68
  -69.89  -19.97  -19.51   -19.5    8.34    8.35   67.02  115.25  168.84  222.17
  278.48  329.29  380.16  485.32  536.28  640.93  669.66  730.47  755.91
  385.89  383.32 381.768 380.096 378.912 378.204 377.754 377.594 377.571 377.712
 378.935 379.467 379.421 382.077 382.225 379.569 380.184 380.906 382.042 383.669
 385.725 387.715 389.816 393.776 395.957 400.936  402.01  404.69 405.711
     365     365     365     365     365     365     365     365     365     365
     365     365     365     365     365     365     365     365     365     365
     365     365     365     365     365     365     365     365     365
BR Coef=-1 , 0 , 0 ,, 0 ,,,0.8,-1,,0,
WSPro=,,,, 1 ,,,, 0 ,,,, 0 ,,,,-1 ,-1 ,-1 , 0 , 0 , 0 , 0 , 0
Culvert=4,1.833,3.33,54.95,0.012,0.2,1,29,1,373.06,-213.91,372.57,-183.83,Culvert #1  , 0 ,4.68
 -213.91 -183.83
BC Culvert Barrel=1,40x22,0
Culvert Bottom n=0.012
Multiple Barrel Culv=2,5,12,39,0.012,0.5,1,10,1,372.69,372.69, 2,Culvert #2  , 0 ,7.78
   -1.11     -14   12.89       0
BC Culvert Barrel=1,12' box #1,0
BC Culvert Barrel=2,12' box #2,0
Culvert Bottom n=0.012
Culvert Bottom Depth=1
Culvert Depth Blocked=1
BC Design=,, 0 ,, 0 ,,,,,,
BC Use User HTab Curves=0
BC User HTab FreeFlow(D)= 0

Type RM Length L Ch R = 1 ,2069    ,220.1,221.15,221.05
BEGIN DESCRIPTION:
DOWN1
END DESCRIPTION:
#Sta/Elev= 30
 -600.99  381.65  -434.1  376.96 -401.92  376.47 -365.72  377.16    -301  376.64
 -200.15  376.92 -197.01  373.49 -185.81  373.33 -184.16  373.45  -178.7   377.3
 -128.68  377.04  -61.49  378.05  -10.06378.1417   -9.82377.8753   -9.78378.3173
   -9.15377.6436   -2.64374.8964       0374.5825    2.86375.0637    8.23378.3363
   55.99  378.36   97.08     379     212  386.74  255.26  386.95   262.7  386.22
  268.42  383.71  275.33  387.03  285.79  388.25  317.14  388.45  327.37  389.08
#Mann= 3 , 0 , 0
 -600.99      .1       0  -10.06    .048       0    8.23      .1       0
#XS Ineff= 2 , 0
       0 -193.26  377.57  15.435       0  377.57
Permanent Ineff=
       F       F
Bank Sta=-10.06,8.23
XS Rating Curve= 0 ,0
Exp/Cntr=0.5,0.3

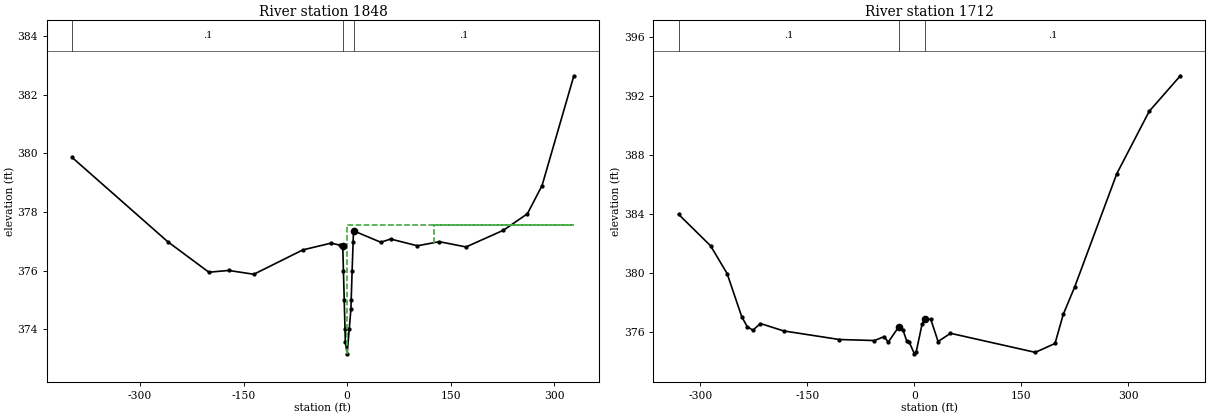
Type RM Length L Ch R = 1 ,1848    ,137.88,136.32,136.5
BEGIN DESCRIPTION:
STA 1848
END DESCRIPTION:
#Sta/Elev= 29
 -398.37  379.86 -259.84  376.99 -200.27  375.95 -171.54  376.01 -135.17  375.88
  -64.17  376.71  -23.38  376.94  -10.02  376.87   -6.38  376.85   -5.38  375.99
   -4.23     375   -3.09     374    -2.6  373.57       0  373.17    2.99     374
    5.47   374.7    5.88  375.02    7.21     376    8.65  376.98    9.21  377.36
   48.76  376.97   62.91  377.08  101.75  376.85  133.53  376.99  172.18  376.81
  226.39  377.38  261.02  377.94  282.24   378.9  328.32  382.64
#Mann= 3 , 0 , 0
 -398.37      .1       0   -6.38    .048       0    9.21      .1       0
#XS Ineff= 2 , 0
       0 -303.76  377.57 125.935       0  377.57
Permanent Ineff=
       F       F
Bank Sta=-6.38,9.21
XS Rating Curve= 0 ,0
Exp/Cntr=0.3,0.1

Type RM Length L Ch R = 1 ,1712    ,628.29,630.76,602.03
BEGIN DESCRIPTION:
LiDAR3
END DESCRIPTION:
#Sta/Elev= 30
 -330.58  383.99 -285.68  381.86 -262.48  379.98 -241.99  377.06 -234.34  376.39
  -226.4  376.15 -215.76   376.6 -183.17   376.1  -105.3  375.52  -55.96  375.45
  -42.13  375.72  -36.73  375.33  -21.92  376.38   -15.8  376.13   -10.9  375.45
   -7.36  375.36       0  374.55    2.63   374.7   10.91  376.59   15.51  376.91
   23.05  376.88   33.23  375.38    50.6  375.94  169.52  374.65  197.13  375.25
  208.67  377.22  224.57  379.06  283.75  386.74   329.2  390.96  372.77  393.36
#Mann= 3 , 0 , 0
 -330.58      .1       0  -21.92    .048       0   15.51      .1       0
Bank Sta=-21.92,15.51
XS Rating Curve= 0 ,0
Exp/Cntr=0.3,0.1